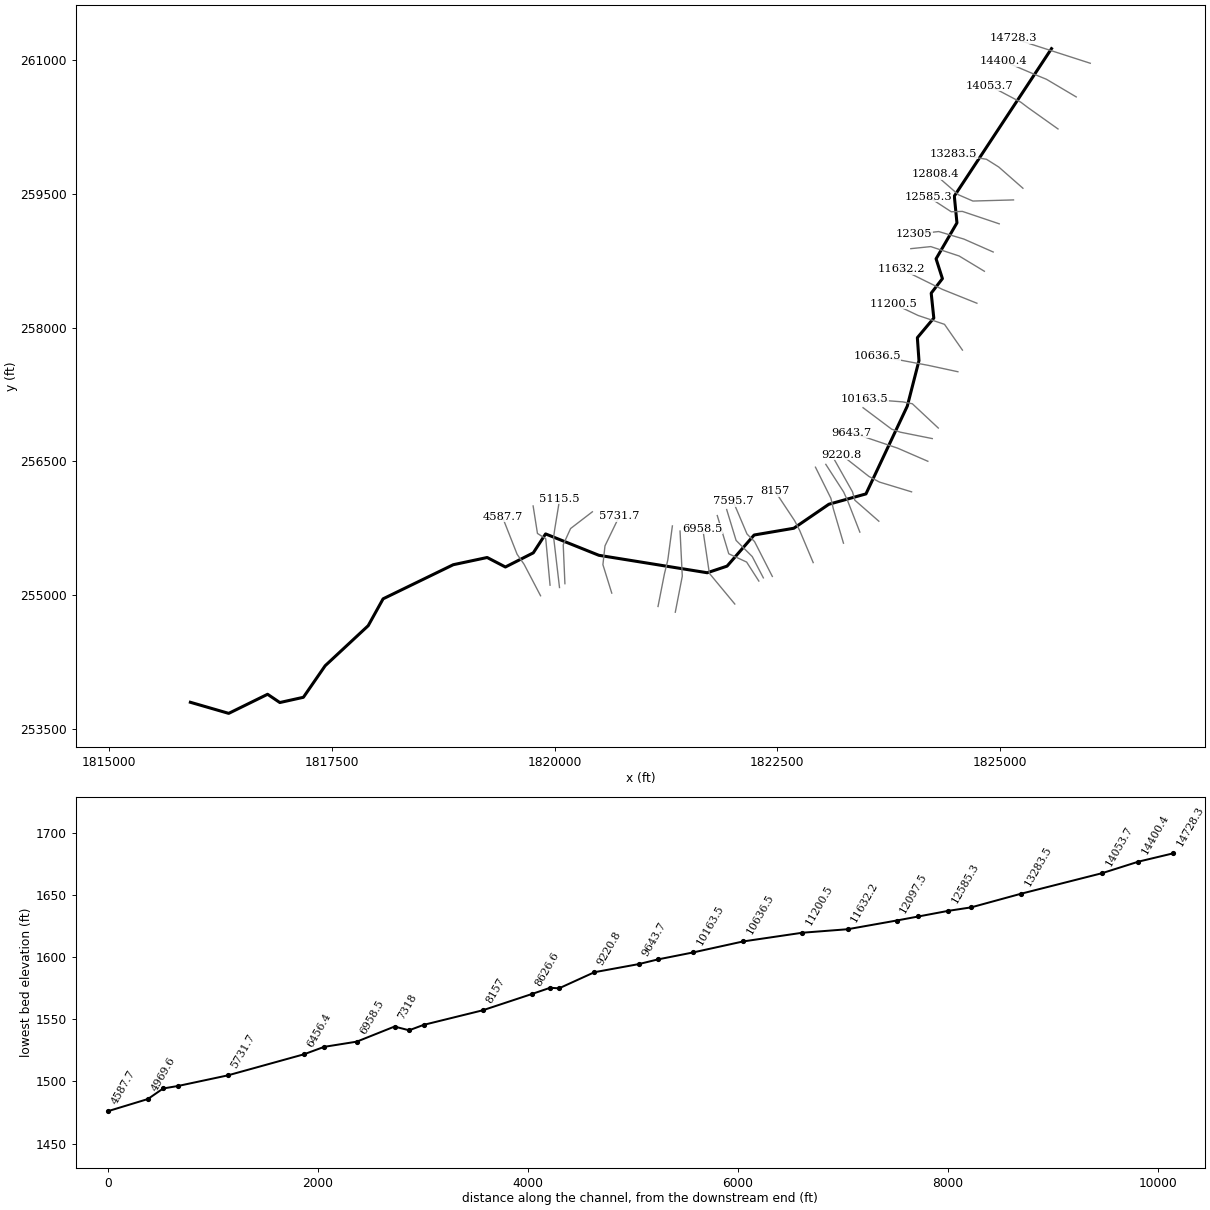
--- GlenFk.prj (project) ---

Proj Title=GlenFk
Current Plan=p01
Default Exp/Contr=0,0
English Units
Geom File=g01
Flow File=f01
Plan File=p01
BEGIN DESCRIPTION:
END DESCRIPTION:
DSS Export Rating Curves= 0
DSS Export Rating Curve Sorted= 0
DSS Export Volume Flow Curves= 0
DXF OffsetX= 0
DXF OffsetY= 0
DXF ScaleX= 0
DXF ScaleY= 0

--- GlenFk.p01 (plan) ---

Plan Title=Floodplain
Program Version=4.00
Geom File=g01
Flow File=f01
K Sum by GR=0
Std Step Tol=0.01
Critical Tol=0.01
Num of Std Step Trials=20
Max Error Tol=0.3
Flow Tol Ratio=0.001
Split Flow NTrial=30
Split Flow Tol=0.02
Split Flow Ratio=0.02
Log Output Level=0
Friction Slope Method=1
Unsteady Friction Slope Method=2
Unsteady Bridges Friction Slope Method=1
Global Log Level=0
CheckData=False
Run HTab=0
Run UNet=0
Run PostProcess=0
UNET Theta=0
UNET Theta Warmup=0
UNET ZTol=0
UNET ZSATol=0
UNET MxIter=0
UNET MaxInSteps=0
UNET DtIC=0
UNET DtMin=0
UNET MaxCRTS=0
UNET WFStab=0
UNET SFStab=0
UNET WFX=0
UNET SFX=0
UNET DSS MLevel=0
UNET DZMax Abort=0
UNET Convert EG Bridges=0
UNET Use Existing IB Tables=0
UNET Froude Limit=0
UNET Froude Power=0
Write IC File=0
Echo Input=False
Echo Output=False
Write Detailed=0

--- GlenFk.f01 (steady flow) ---

Flow Title=NFF Regression Equation
Program Version=4.00
Number of Profiles=1
Profile Names=P100yr
River Rch & RM=GlenFk,Main      ,14728.3
607.5859
River Rch & RM=GlenFk,Main      ,14400.4
630.3809
River Rch & RM=GlenFk,Main      ,12585.3
685.9554
River Rch & RM=GlenFk,Main      ,12305
776.6137
River Rch & RM=GlenFk,Main      ,11632.2
812.7718
River Rch & RM=GlenFk,Main      ,9220.8
864.0924
River Rch & RM=GlenFk,Main      ,8884.1
959.2371
River Rch & RM=GlenFk,Main      ,6456.4
1049.814
River Rch & RM=GlenFk,Main      ,4969.6
1139.483
River Rch & RM=GlenFk,Main      ,2924.3
1182.238
River Rch & RM=GlenFk,Main      ,2562
1575.728
River Rch & RM=GlenFk,Main      ,160.5
1621.366
Boundary for River Rch & Prof#=GlenFk,Main      ,1
Up Type=0
Dn Type=3
Dn Slope=0.044279

--- GlenFk.g01 (geometry) ---

Geom Title=USGS 10m DEM
Program Version=4.00

River Reach=GlenFk          ,Main
Reach XY= 30
     1825575.533      261127.865      1824485.24      259474.725
     1824514.773      259174.252      1824280.64       258771.63
     1824351.755      258549.532     1824225.936      258386.514
     1824255.114        258107.3     1824070.618      257887.268
     1824088.764      257630.198     1823957.887      257120.664
     1823493.997      256135.992     1823078.024       256020.03
     1822684.378      255750.877     1822239.672      255675.253
     1821936.028      255326.374     1821713.929      255251.976
     1820497.642      255447.822     1819899.945       255687.42
     1819762.091      255475.169     1819449.185      255316.527
     1819244.669      255423.043     1818863.905      255342.032
     1818077.209      254959.857     1817910.002      254658.464
     1817427.314      254209.649     1817182.947        253855.8
     1816918.618      253797.127     1816781.312      253889.672
       1816345.2      253675.548      1815915.11      253800.013

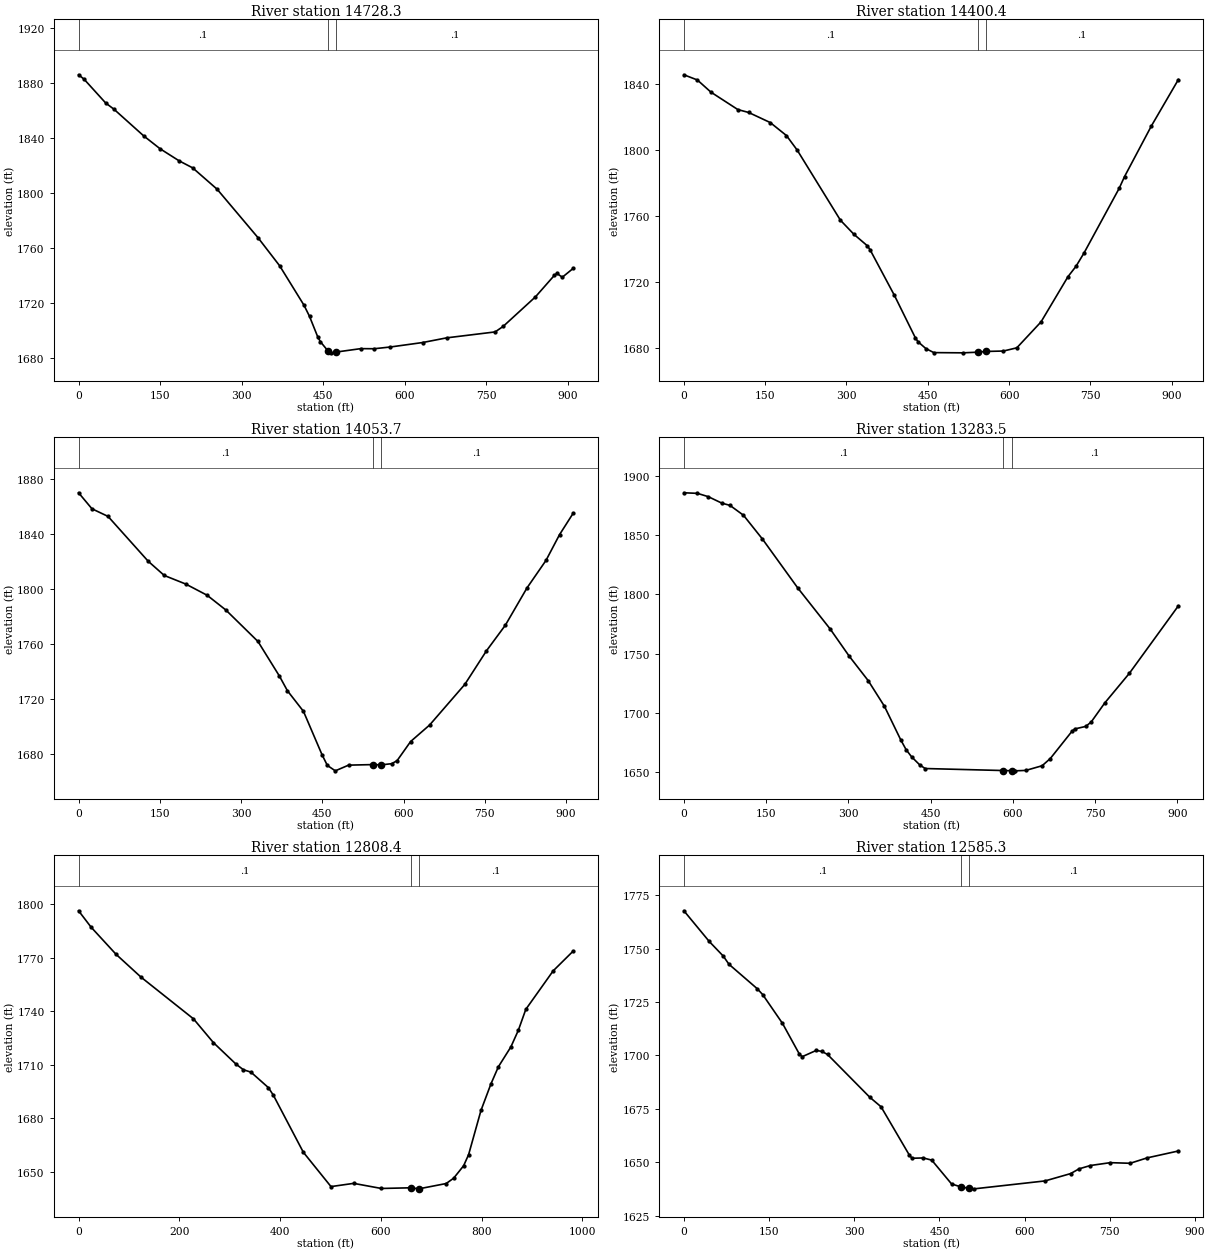
Type RM Length L Ch R = 1 ,14728.3 ,330,327.9,325.8
XS GIS Cut Line= 3
     1826010.347      260963.931      1825577.32      261103.616
     1825144.292      261243.302
#Sta/Elev= 30
       0 1885.89      10 1882.72      50 1865.34      65 1860.91     120 1841.44
     150 1832.14     185 1823.38     210 1818.25     255 1802.73     330 1767.63
     370 1747.14     415 1718.37     425 1710.37     440 1695.59     445 1691.96
     459 1685.28   464.9 1683.88     474 1684.45   519.3 1686.93     544 1686.86
   573.7 1688.12     633 1691.36   677.6 1694.78   766.6 1699.08   781.4  1703.1
   840.8 1724.56   875.4 1740.09   880.3 1741.57   890.2  1738.8     910 1745.16
#Mann= 3 , 0 , 0
       0      .1       0     459    .045       0     474      .1       0
Bank Sta=459,474
XS Rating Curve= 0 ,0
Exp/Cntr=0.3,0.1

Type RM Length L Ch R = 1 ,14400.4 ,348.7,346.8,344.9
XS GIS Cut Line= 4
     1825852.839       260586.48     1825518.719      260784.436
     1825415.324      260826.638     1825035.953       260988.19
#Sta/Elev= 30
       0  1845.3    24.9 1842.15    49.8 1834.83    99.6 1824.26   119.5 1822.52
   159.3 1816.43   189.2 1808.58   209.1 1799.76   288.8 1757.41   313.7 1748.89
   338.6 1741.92   343.6  1739.5   388.4 1711.99   427.2 1686.24   432.1 1683.91
   446.6 1679.79   461.2 1677.38   514.9 1677.24   541.9 1677.63   556.9 1678.08
   589.5 1678.33   614.3 1680.27     659 1695.95   708.7 1723.28   723.6 1729.58
   738.5  1737.7   803.1 1776.62     813 1783.73   862.7 1814.44   912.4  1842.4
#Mann= 3 , 0 , 0
       0      .1       0   541.9    .045       0   556.9      .1       0
Bank Sta=541.9,556.9
XS Rating Curve= 0 ,0
Exp/Cntr=0.3,0.1

Type RM Length L Ch R = 1 ,14053.7 ,762.3,770.2,778.2
XS GIS Cut Line= 4
     1825648.341      260227.462     1825309.818       260467.92
     1825231.744      260527.003     1824878.254      260713.885
#Sta/Elev= 30
       0 1869.99    24.7 1858.36    54.4 1852.82   128.5 1820.26   158.2 1809.91
   197.7  1803.7   237.3 1795.54   271.9 1784.81   331.2 1761.94   370.7 1736.87
   385.6 1726.13   415.2 1711.17   449.5 1679.65   459.3 1671.87     474 1667.93
   498.5 1672.07   543.1 1672.47   558.1 1672.27   558.1 1672.26   578.1 1673.12
   588.1 1675.34   613.1 1689.24   648.1 1701.21   713.1 1730.73     753  1755.1
     788 1773.78     828 1800.89     863 1820.84     888 1839.55     913    1855
#Mann= 3 , 0 , 0
       0      .1       0   543.1    .045       0   558.1      .1       0
Bank Sta=543.1,558.1
XS Rating Curve= 0 ,0
Exp/Cntr=0.3,0.1

Type RM Length L Ch R = 1 ,13283.5 ,488.2,475.1,461.8
XS GIS Cut Line= 4
     1825254.956      259562.685     1824983.789      259800.664
     1824845.595      259887.641     1824472.811      259948.857
#Sta/Elev= 30
       0 1885.46    24.7 1884.98    44.5 1882.18    69.2 1876.74      84 1874.87
   108.7 1866.53   143.3 1846.49   207.6 1805.38   266.9 1770.72   301.5 1747.92
   336.1 1727.34   365.7 1705.77   395.4 1677.55   405.3 1669.18   415.2 1663.23
   430.1  1656.4     440 1653.34   582.7 1651.64   597.7 1651.48   603.6 1651.39
   623.5 1651.74   653.3 1655.68   668.2 1661.73     708 1684.82     713 1686.68
   732.8 1688.79   742.8 1692.51   767.6 1708.57   812.4 1733.48   901.8 1790.29
#Mann= 3 , 0 , 0
       0      .1       0   582.7    .045       0   597.7      .1       0
Bank Sta=582.7,597.7
XS Rating Curve= 0 ,0
Exp/Cntr=0.3,0.1

Type RM Length L Ch R = 1 ,12808.4 ,205.9,223.1,240.3
XS GIS Cut Line= 4
      1825149.45      259431.858     1824693.667      259419.198
     1824533.299      259488.831     1824268.811      259718.872
#Sta/Elev= 30
       0 1796.43    24.8 1787.24    74.3 1772.02   123.9 1759.19     228 1735.79
   267.6 1722.44   312.2 1710.43   327.1 1707.22     342 1705.89   376.7 1697.18
   386.6  1692.9     446 1660.93   500.9 1641.65   545.9 1643.46   600.8  1640.6
   659.9 1640.98   674.9  1640.4   675.2 1640.39   729.5 1643.37   744.3 1646.36
   764.1 1653.34     774 1659.59   798.6 1684.43   818.4 1699.34   833.2 1708.94
   857.9 1720.04   872.7 1729.37   887.5 1741.11   941.8 1762.71   981.3 1773.75
#Mann= 3 , 0 , 0
       0      .1       0   659.9    .045       0   674.9      .1       0
Bank Sta=659.9,674.9
XS Rating Curve= 0 ,0
Exp/Cntr=0.3,0.1

Type RM Length L Ch R = 1 ,12585.3 ,287.5,280.2,272.9
XS GIS Cut Line= 4
     1824989.082      259163.875     1824575.502      259303.142
     1824451.005      259298.922     1824191.462       259467.73
#Sta/Elev= 30
       0 1767.72    44.6 1753.36    69.4 1746.48    79.4 1742.66   128.9 1731.28
   138.8 1728.45   173.6 1714.99   203.3 1700.61   208.3 1699.39   233.1 1702.33
     243 1701.85   252.9 1700.43   327.3 1680.39   347.1 1675.94   396.7 1653.41
   401.7 1651.82   421.5 1651.97   436.4 1650.94   471.3 1639.78   487.5 1638.43
   502.5 1637.71   511.1  1637.5   635.9 1641.21   680.8 1644.63   695.8 1646.87
   715.8 1648.43   750.7 1649.76   785.7 1649.47   815.6    1652   870.6 1655.23
#Mann= 3 , 0 , 0
       0      .1       0   487.5    .045       0   502.5      .1       0
Bank Sta=487.5,502.5
XS Rating Curve= 0 ,0
Exp/Cntr=0.3,0.1

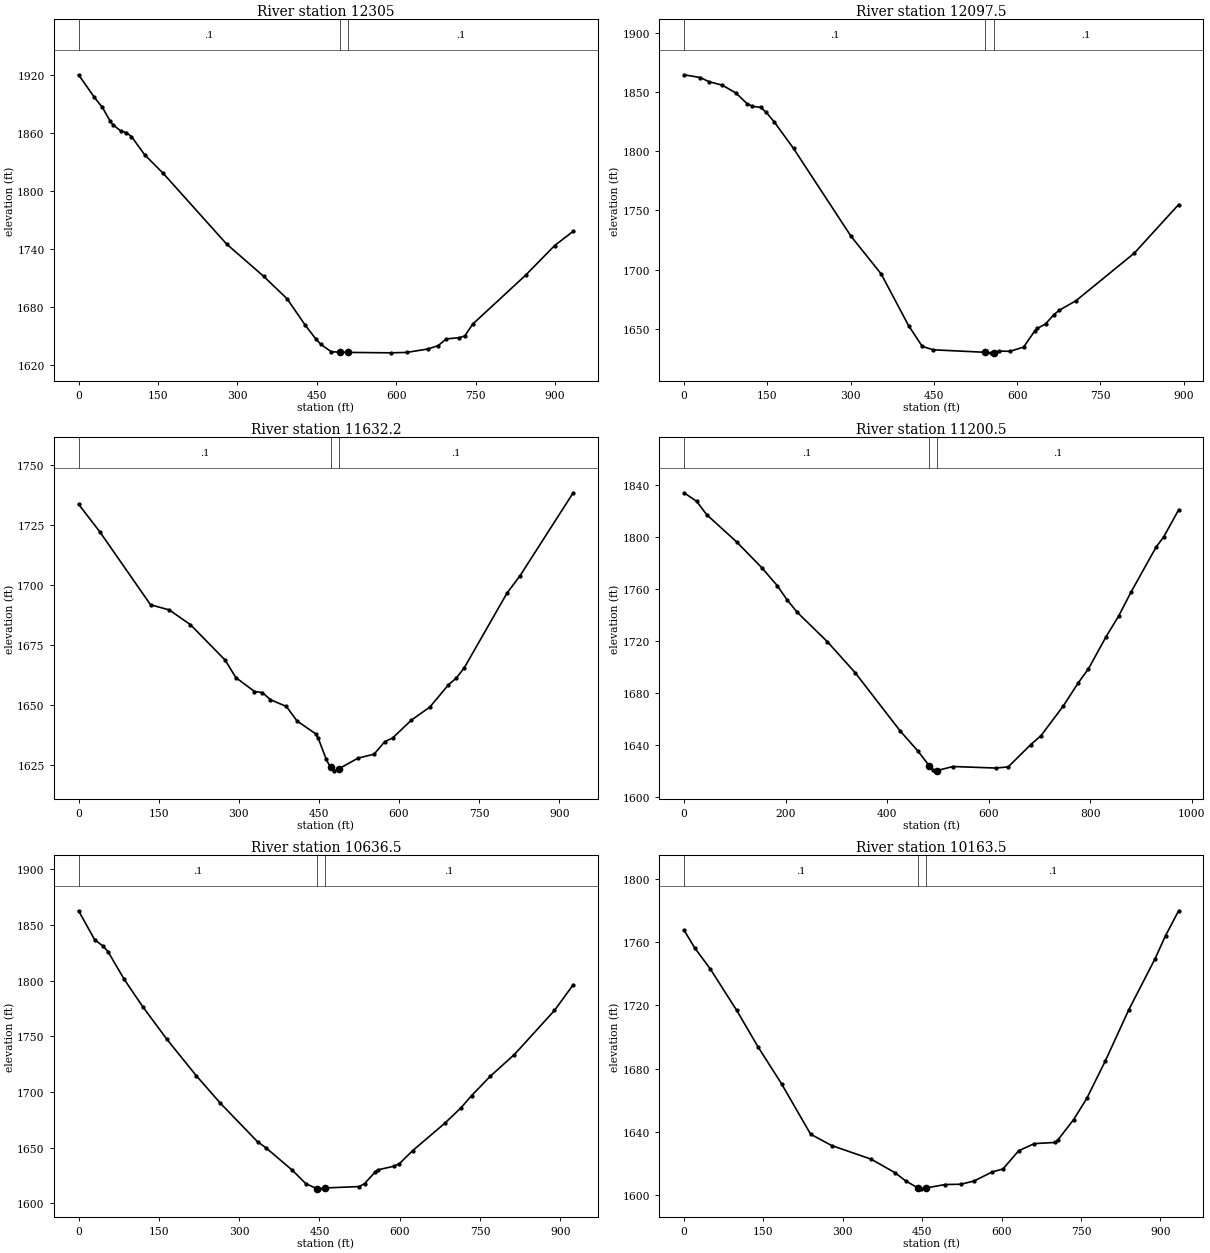
Type RM Length L Ch R = 1 ,12305   ,208.3,207.6,206.8
XS GIS Cut Line= 4
     1824921.443      258847.996     1824592.382      258992.956
     1824309.628      259077.361     1824031.622       259045.58
#Sta/Elev= 30
       0  1920.4      30 1896.92      45 1886.68    59.9 1872.26    64.9 1868.79
    79.9 1862.22    89.9 1860.73    99.9 1856.61   124.8 1837.75   159.8  1818.6
   279.7 1745.43   349.6 1712.17     394 1688.87   428.4 1661.48   448.1 1647.49
   457.9 1641.75   477.6 1634.07   493.5 1633.87   508.5 1633.49   590.7 1633.03
   620.2  1633.5   659.7 1636.98   679.6 1640.52   694.6  1647.4   719.6 1648.73
   729.6 1650.47   744.6 1662.68   844.5 1713.21   899.5 1743.93   934.5 1758.64
#Mann= 3 , 0 , 0
       0      .1       0   493.5    .045       0   508.5      .1       0
Bank Sta=493.5,508.5
XS Rating Curve= 0 ,0
Exp/Cntr=0.3,0.1

Type RM Length L Ch R = 1 ,12097.5 ,468.9,465.3,461.6
XS GIS Cut Line= 4
     1824822.384      258632.128      1824539.63      258803.047
     1824221.004      258908.552     1823997.333      258885.341
#Sta/Elev= 30
       0 1864.59    29.6 1862.24    44.4 1858.84      69 1855.82    93.7  1849.1
   113.4 1840.26   123.3 1837.95   138.1 1837.08   147.9 1832.94   162.7 1824.64
   197.2 1802.39   300.8 1728.21   355.1 1696.38   404.4 1652.81   429.1 1635.19
   448.9 1632.33   542.7  1630.2   552.5 1629.76   557.7 1629.93   567.3 1631.23
   587.1 1631.05   611.7 1634.63   631.5 1648.09   636.4  1650.4   651.2  1654.2
     666 1661.95     676 1665.75     706 1673.79     811 1713.94   890.9 1755.02
#Mann= 3 , 0 , 0
       0      .1       0   542.7    .045       0   557.7      .1       0
Bank Sta=542.7,557.7
XS Rating Curve= 0 ,0
Exp/Cntr=0.3,0.1

Type RM Length L Ch R = 1 ,11632.2 ,429.5,431.6,433.8
XS GIS Cut Line= 3
     1824738.694      258273.592      1824349.72      258429.558
      1823895.13      258654.051
#Sta/Elev= 30
       0 1733.71    39.9 1722.21   134.7 1691.88   169.6 1689.75   209.5 1683.59
   274.4 1668.85   294.4  1661.6   329.3 1655.78   344.2 1655.34   359.2 1652.37
   389.1 1649.55   409.1 1643.51   443.9 1638.17   448.9 1636.24   463.8 1627.48
   471.8 1624.18   478.7 1622.76   486.8 1623.56   523.5 1628.07   553.3 1629.69
   573.2 1634.89   588.1 1636.45   622.9 1643.84   657.7  1649.3   692.5 1658.57
   707.4 1661.41   722.3  1665.7   801.8  1696.6   826.7    1704   926.1 1738.49
#Mann= 3 , 0 , 0
       0      .1       0   471.8    .045       0   486.8      .1       0
Bank Sta=471.8,486.8
XS Rating Curve= 0 ,0
Exp/Cntr=0.3,0.1

Type RM Length L Ch R = 1 ,11200.5 ,560.6,564.1,567.6
XS GIS Cut Line= 4
     1824576.237      257748.443     1824375.042      258037.078
     1824079.627      258136.253     1823798.564      258269.334
#Sta/Elev= 30
       0 1833.99    24.8 1827.45    44.6 1817.16   104.1    1796   153.6 1776.13
   183.4  1762.6   203.2 1751.47     223 1741.99   282.5  1719.3     337 1695.56
     426 1650.55   460.7 1635.21   483.1 1623.81   490.3 1620.77   495.3 1619.93
   498.1 1620.09   529.9 1623.26     614 1622.08   638.7 1622.98   683.2 1640.18
     703 1646.87   747.4 1670.02     777 1687.89   796.7 1698.47   831.3 1723.11
     856 1738.93   880.6 1757.54     930  1792.2   944.8 1799.93   974.4 1820.86
#Mann= 3 , 0 , 0
       0      .1       0   483.1    .045       0   498.1      .1       0
Bank Sta=483.1,498.1
XS Rating Curve= 0 ,0
Exp/Cntr=0.3,0.1

Type RM Length L Ch R = 1 ,10636.5 ,473.3,473,472.6
XS GIS Cut Line= 3
     1824525.523      257505.562     1824193.573      257577.076
     1823618.991       257684.47
#Sta/Elev= 30
       0 1862.88      30 1836.91    44.9  1831.4    54.9 1826.24    84.9 1801.49
   119.8 1776.72   164.8 1747.46   219.7 1714.73   264.7    1690   334.6 1655.12
   349.6 1649.99   399.5 1629.55   424.5 1617.57   444.7 1613.14   449.5  1612.9
   459.7 1613.68   524.4 1614.95   534.4 1617.64   554.4 1628.18   559.4 1629.98
   589.4 1633.28   599.4 1635.57   624.3 1647.29   684.3 1671.93   714.3 1685.67
   734.2 1696.69   769.2 1714.14   814.2 1733.64   889.1 1773.28   924.1 1796.35
#Mann= 3 , 0 , 0
       0      .1       0   444.7    .045       0   459.7      .1       0
Bank Sta=444.7,459.7
XS Rating Curve= 0 ,0
Exp/Cntr=0.3,0.1

Type RM Length L Ch R = 1 ,10163.5 ,342.8,339.7,336.5
XS GIS Cut Line= 4
     1824305.408       256874.41     1824014.214      257146.614
     1823906.598      257167.715     1823481.519       257200.08
#Sta/Elev= 30
       0  1767.6    19.9 1756.56    49.8    1743    99.6 1716.87   139.5 1694.01
   184.4  1670.4   239.2 1638.63     279 1631.46   353.8 1622.82   398.6 1614.29
   418.6 1609.17   442.9 1604.45   448.5 1604.09   457.9 1604.67   493.3 1606.81
   523.1    1607   547.9 1609.02   582.6 1614.83   602.5  1616.6   632.2 1628.13
   661.9 1632.68   701.6 1633.42   706.6 1635.08   736.3 1647.91   761.1 1661.32
   795.8 1684.77   840.4 1717.28     890 1749.52   909.8 1764.11   934.6 1779.86
#Mann= 3 , 0 , 0
       0      .1       0   442.9    .045       0   457.9      .1       0
Bank Sta=442.9,457.9
XS Rating Curve= 0 ,0
Exp/Cntr=0.3,0.1

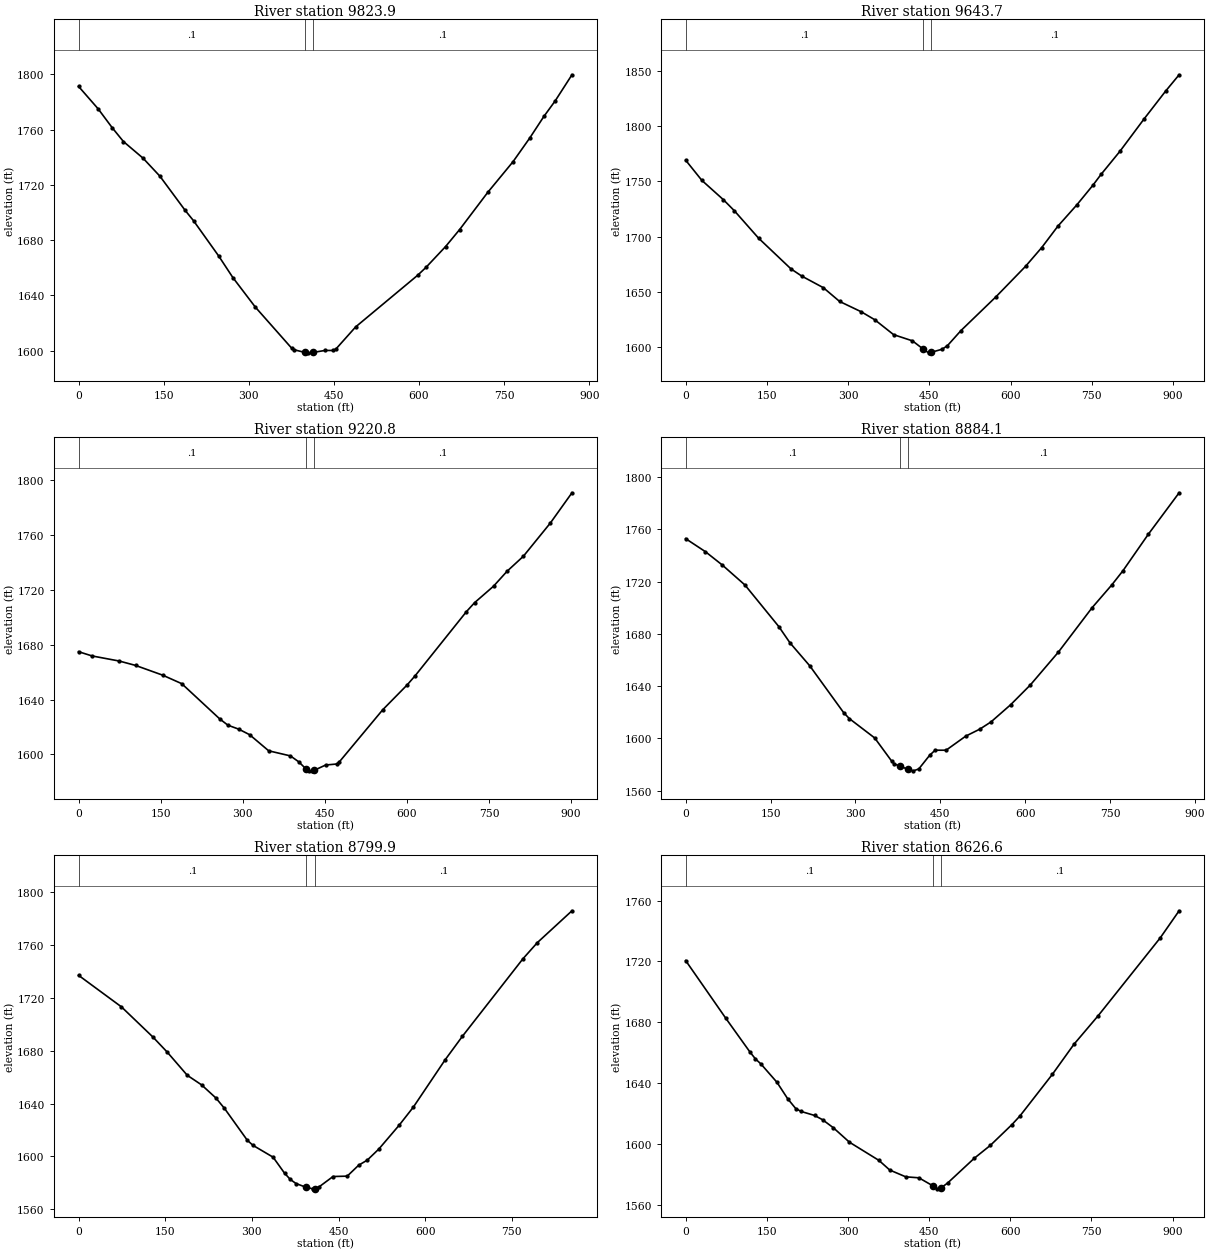
Type RM Length L Ch R = 1 ,9823.9  ,180,180.2,180.4
XS GIS Cut Line= 4
     1824237.885      256756.245     1823879.167      256827.988
     1823782.102       256861.75     1823461.366      257102.302
#Sta/Elev= 30
       0 1791.27    34.6 1774.99    59.3 1761.36    79.1 1751.35   113.7 1739.29
   143.4 1726.25   187.8 1701.55   202.7    1694   247.2 1668.36   271.9  1652.9
   311.4 1631.57   375.6 1601.74   380.5 1600.55   398.9 1598.68     405 1598.39
   413.9 1598.73   434.3 1600.12     449  1600.1   453.9 1601.32   488.4 1617.19
   597.3 1654.44   612.1 1660.18   646.8 1675.33   671.5 1687.61     721  1714.5
   765.6 1736.73   795.3 1754.01     820 1769.51   839.8  1780.7   869.5 1799.66
#Mann= 3 , 0 , 0
       0      .1       0   398.9    .045       0   413.9      .1       0
Bank Sta=398.9,413.9
XS Rating Curve= 0 ,0
Exp/Cntr=0.3,0.1

Type RM Length L Ch R = 1 ,9643.7  ,426.6,422.9,419.2
XS GIS Cut Line= 3
     1824188.327       256501.86     1823849.625      256648.629
     1823335.996      256822.538
#Sta/Elev= 30
       0 1769.22    29.9 1750.94    69.8 1733.37    89.8 1723.48   134.7 1698.55
   194.5 1670.72   214.5 1664.18   254.4 1653.65   284.3 1641.23   324.2 1631.88
   349.2 1624.66   384.1 1611.12   418.9 1605.51   438.5 1598.13   448.7 1594.65
   453.5 1595.15   473.6 1597.89   483.6 1601.21   508.4 1614.79   573.1 1645.43
   627.8 1673.07   657.7 1690.09   687.5 1709.45   722.4 1728.68   752.2 1746.54
   767.1 1756.29     802 1777.23   846.7 1806.63   886.5 1831.85   911.4 1846.63
#Mann= 3 , 0 , 0
       0      .1       0   438.5    .045       0   453.5      .1       0
Bank Sta=438.5,453.5
XS Rating Curve= 0 ,0
Exp/Cntr=0.3,0.1

Type RM Length L Ch R = 1 ,9220.8  ,355.2,336.7,318.3
XS GIS Cut Line= 4
     1824005.773      256159.085     1823644.945       256268.81
     1823526.779      256332.113     1823219.714      256573.047
#Sta/Elev= 30
       0 1674.81    24.8  1671.7    74.4    1668   104.2 1664.81   153.8 1657.71
   188.6 1651.52     258 1625.87   272.9 1621.31   292.8 1618.41   312.6 1614.38
   347.4 1602.67   387.1 1598.96     402 1594.75   415.7 1589.46   421.8 1588.16
   426.8 1588.09   430.7 1588.51   451.6 1592.34   471.5 1593.05   476.4 1594.57
   555.7 1632.51   600.1  1650.5     615  1657.3   708.8 1704.01   723.6 1710.48
   758.2 1722.46   782.9 1733.33   812.6 1744.21     862 1768.44   901.5 1790.45
#Mann= 3 , 0 , 0
       0      .1       0   415.7    .045       0   430.7      .1       0
Bank Sta=415.7,430.7
XS Rating Curve= 0 ,0
Exp/Cntr=0.3,0.1

Type RM Length L Ch R = 1 ,8884.1  ,80.2,84.2,88.2
XS GIS Cut Line= 4
     1823638.615      255829.908     1823368.521       256066.24
       1823343.2      256159.085      1823138.52      256522.023
#Sta/Elev= 30
       0  1752.9    34.9 1742.92    64.8 1732.68   104.7 1717.43   164.5 1685.61
   184.4 1673.06   219.3 1655.49   279.1 1619.68   289.1 1615.13     334 1600.27
   363.7 1582.69   368.5  1580.4   377.8 1578.82   392.8 1576.26   402.2  1575.1
   411.8 1576.52   431.1 1587.02   440.7  1590.9   460.1  1590.9   494.8 1601.67
   519.6 1607.02   539.4 1612.54   574.2 1625.74   608.9 1640.84   658.5 1666.02
     718    1700   752.8 1717.44   772.6 1728.35   817.2 1756.16   871.8 1788.03
#Mann= 3 , 0 , 0
       0      .1       0   377.8    .045       0   392.8      .1       0
Bank Sta=377.8,392.8
XS Rating Curve= 0 ,0
Exp/Cntr=0.3,0.1

Type RM Length L Ch R = 1 ,8799.9  ,178.2,173.3,168.4
XS GIS Cut Line= 4
     1823425.494      255707.522     1823290.447      256053.579
     1823244.025      256156.974     1823043.565       256467.16
#Sta/Elev= 30
       0 1736.87    74.3 1713.02   128.8 1690.22   153.5 1678.86   188.2 1661.34
     213 1654.09   237.7 1644.22   252.6 1636.35   292.2 1612.22   302.1 1608.38
   336.8 1599.46   356.6 1587.39   366.5 1582.68   376.4 1579.58   393.9 1576.71
     406 1575.56   408.9 1575.77   415.8 1576.87   440.5 1584.86   465.1 1585.15
   484.8 1593.38   499.8 1597.25   519.8 1605.63   554.7 1623.47   579.6 1637.34
   634.5    1673   664.5 1690.83   769.3 1749.39   794.2 1761.57   854.1 1785.61
#Mann= 3 , 0 , 0
       0      .1       0   393.9    .045       0   408.9      .1       0
Bank Sta=393.9,408.9
XS Rating Curve= 0 ,0
Exp/Cntr=0.3,0.1

Type RM Length L Ch R = 1 ,8626.6  ,463.9,469.6,475.3
XS GIS Cut Line= 4
     1823241.757       255583.65     1823127.969      255969.175
     1823100.538      256087.341     1822927.509      256435.508
#Sta/Elev= 30
       0 1720.55    74.4 1682.52   119.1 1660.33     129 1655.92     139 1652.65
   168.7 1640.59   188.6 1629.74   203.5 1623.29   213.4  1621.4   238.2 1618.78
   253.1 1615.96   272.9 1610.71   302.7  1601.2   357.3 1589.23   377.2 1582.91
   406.8 1578.44   431.1  1577.8   457.2 1572.47     465 1570.55   472.2 1571.21
   484.5 1574.46   533.2 1590.56   563.2 1599.12     603 1612.72     618 1618.49
   677.8 1645.78   717.7 1665.54   762.5 1684.31   877.2 1735.46   912.1 1753.27
#Mann= 3 , 0 , 0
       0      .1       0   457.2    .045       0   472.2      .1       0
Bank Sta=457.2,472.2
XS Rating Curve= 0 ,0
Exp/Cntr=0.3,0.1

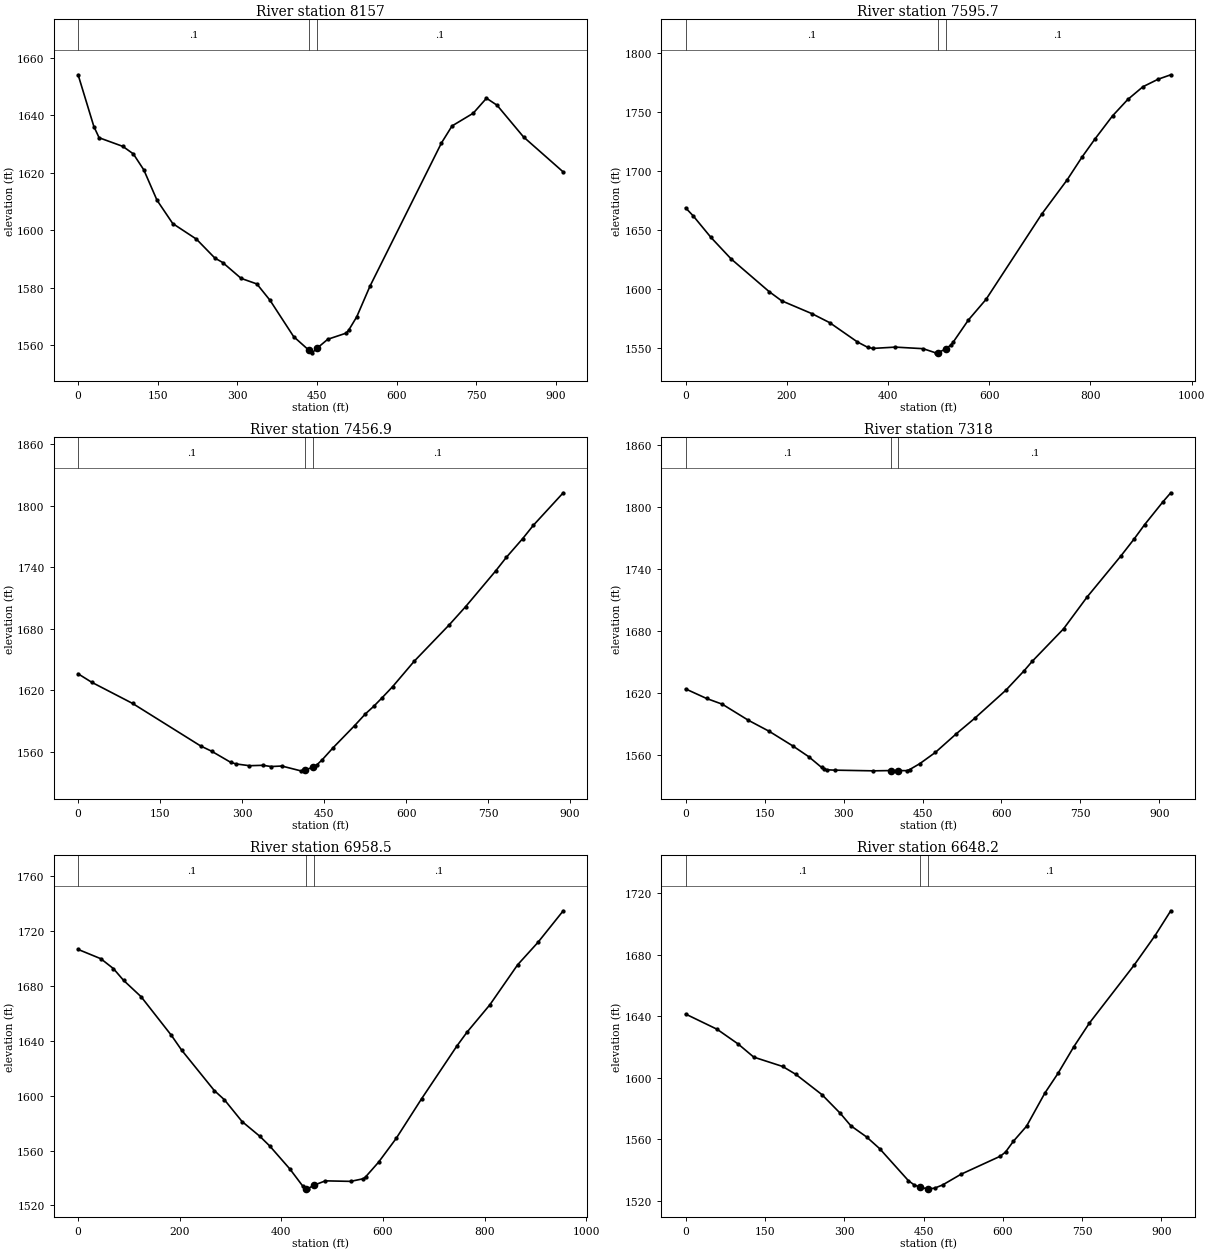
Type RM Length L Ch R = 1 ,8157    ,554.4,561.2,568
XS GIS Cut Line= 4
     1822902.104      255365.872      1822750.26      255726.513
     1822693.288      255836.238     1822472.628      256168.787
#Sta/Elev= 30
       0 1654.17    29.7 1636.15    39.6 1632.25    84.2 1629.25     104 1626.64
   123.8 1621.06   148.6 1610.52   178.3 1602.38   222.9 1596.96   257.6 1590.38
   272.4 1588.82   307.1  1583.3   336.8 1581.36   361.6 1575.66   406.1 1563.02
   434.7 1558.31   440.8 1557.38   449.7 1558.92   470.4  1562.1     505 1564.24
     510 1565.34   524.9  1569.9   549.9 1580.59   684.6 1630.45   704.5 1636.36
   744.4 1640.79   769.4 1646.01   789.3 1643.57   839.2 1632.53     914 1620.34
#Mann= 3 , 0 , 0
       0      .1       0   434.7    .045       0   449.7      .1       0
Bank Sta=434.7,449.7
XS Rating Curve= 0 ,0
Exp/Cntr=0.3,0.1

Type RM Length L Ch R = 1 ,7595.7  ,138.6,138.9,139.2
XS GIS Cut Line= 4
     1822443.671       255210.71     1822243.835      255602.017
     1822159.431      255686.421     1822003.359      256054.627
#Sta/Elev= 30
       0 1668.52      15  1661.7    49.9 1643.54    89.9 1625.24   164.8 1597.62
   189.7 1589.77   249.6 1578.86   284.6 1571.25   339.5 1554.88   359.5  1550.4
   369.5  1549.4   414.4 1550.51   469.2 1549.19   494.1 1545.66     499 1545.82
     514 1548.97     514 1548.98   523.9 1552.26   528.9 1554.84   558.8  1573.5
   593.7    1591   703.7 1663.22   753.7 1692.12   783.7 1711.81   808.7 1726.78
   843.7 1746.52   873.7 1760.37   903.7 1771.18   933.7 1777.53   958.7 1781.31
#Mann= 3 , 0 , 0
       0      .1       0     499    .045       0     514      .1       0
Bank Sta=499,514
XS Rating Curve= 0 ,0
Exp/Cntr=0.3,0.1

Type RM Length L Ch R = 1 ,7456.9  ,130.9,138.8,146.8
XS GIS Cut Line= 4
      1822343.01      255194.766     1822218.514      255433.208
     1822037.045      255614.677     1821931.539      255960.735
#Sta/Elev= 30
       0 1635.97    24.9  1627.7    99.6 1607.07   224.2 1565.53   244.1 1560.46
   278.9 1549.65   288.7 1548.04   313.4 1546.29   338.1 1546.68   352.9 1545.48
   372.6 1545.97   407.2 1541.28   415.3 1542.13   430.3 1545.01   436.8 1547.18
   446.7 1552.19   466.4 1563.82   505.9 1585.47   525.6 1596.91   540.5 1604.11
   555.4 1612.22   575.2 1623.36   614.8 1648.24   679.3    1684     709  1701.6
   763.5 1736.16   783.3 1749.59   813.1 1767.81   832.9 1780.98   887.4 1812.61
#Mann= 3 , 0 , 0
       0      .1       0   415.3    .045       0   430.3      .1       0
Bank Sta=415.3,430.3
XS Rating Curve= 0 ,0
Exp/Cntr=0.3,0.1

Type RM Length L Ch R = 1 ,7318    ,373.2,359.5,337.9
XS GIS Cut Line= 4
     1822292.367      255158.895     1822155.211      255372.015
     1821954.751       255464.86     1821826.034      255893.211
#Sta/Elev= 30
       0 1623.72    39.8 1614.45    69.6 1608.92   119.3 1593.29     159 1582.55
   203.8 1568.37   233.6 1558.09   258.4 1547.54   263.3 1546.13   268.2 1545.32
   282.9 1544.96   356.5 1544.29   389.2 1544.56   404.2 1544.55   420.4 1544.47
   425.3 1545.45   444.9 1551.28   474.4 1562.15   514.1 1580.19   548.9 1595.13
   608.5 1622.54   643.3  1641.5   658.2 1650.38   717.9 1681.97   762.6 1712.82
   827.2 1752.89   852.1  1769.2   871.9 1783.01   906.7 1805.15   921.6 1813.93
#Mann= 3 , 0 , 0
       0      .1       0   389.2    .045       0   404.2      .1       0
Bank Sta=389.2,404.2
XS Rating Curve= 0 ,0
Exp/Cntr=0.3,0.1

Type RM Length L Ch R = 1 ,6958.5  ,318.9,310.3,309.1
XS GIS Cut Line= 3
     1822022.597      254901.545      1821737.41      255245.409
     1821662.663      255747.825
#Sta/Elev= 30
       0 1706.54    44.7 1699.75    69.5 1692.55    89.4 1684.02   124.1 1672.02
   183.7 1643.87   203.5 1633.29     268 1603.72   287.9 1597.03   322.6 1581.17
   357.4 1570.47   377.2  1563.3     417 1546.46   441.8 1534.27   448.8 1532.15
   451.7 1532.12   463.8 1534.72   486.6 1537.94   536.4 1537.56   561.3 1539.48
   566.2 1541.01   591.2  1551.5     626 1568.89   675.8 1597.66   745.5 1636.22
   765.4 1646.28   810.3  1666.2     865 1695.36   904.9 1711.65   954.7 1734.68
#Mann= 3 , 0 , 0
       0      .1       0   448.8    .045       0   463.8      .1       0
Bank Sta=448.8,463.8
XS Rating Curve= 0 ,0
Exp/Cntr=0.3,0.1

Type RM Length L Ch R = 1 ,6648.2  ,199.9,191.8,184.2
XS GIS Cut Line= 3
     1821355.084      254809.721     1821433.555      255213.757
     1821408.435      255719.173
#Sta/Elev= 30
       0 1641.46    59.5 1631.58    99.2 1622.05   128.9 1613.48   183.5 1607.42
   208.3 1602.32   257.9  1589.1   292.6 1576.95   312.4 1568.92   342.2 1561.65
     367 1554.03   421.5 1533.19   431.4 1530.71   443.5 1528.84   458.5 1527.95
   461.2 1527.93   471.1 1528.41     486 1530.44   520.7 1537.38   595.2 1549.13
   605.1 1551.83     620 1558.86   644.8  1568.6   679.5 1590.15   704.3 1602.93
   734.1 1620.17   763.8 1635.66   848.2 1673.19   887.9 1692.45   917.6 1708.55
#Mann= 3 , 0 , 0
       0      .1       0   443.5    .045       0   458.5      .1       0
Bank Sta=443.5,458.5
XS Rating Curve= 0 ,0
Exp/Cntr=0.3,0.1

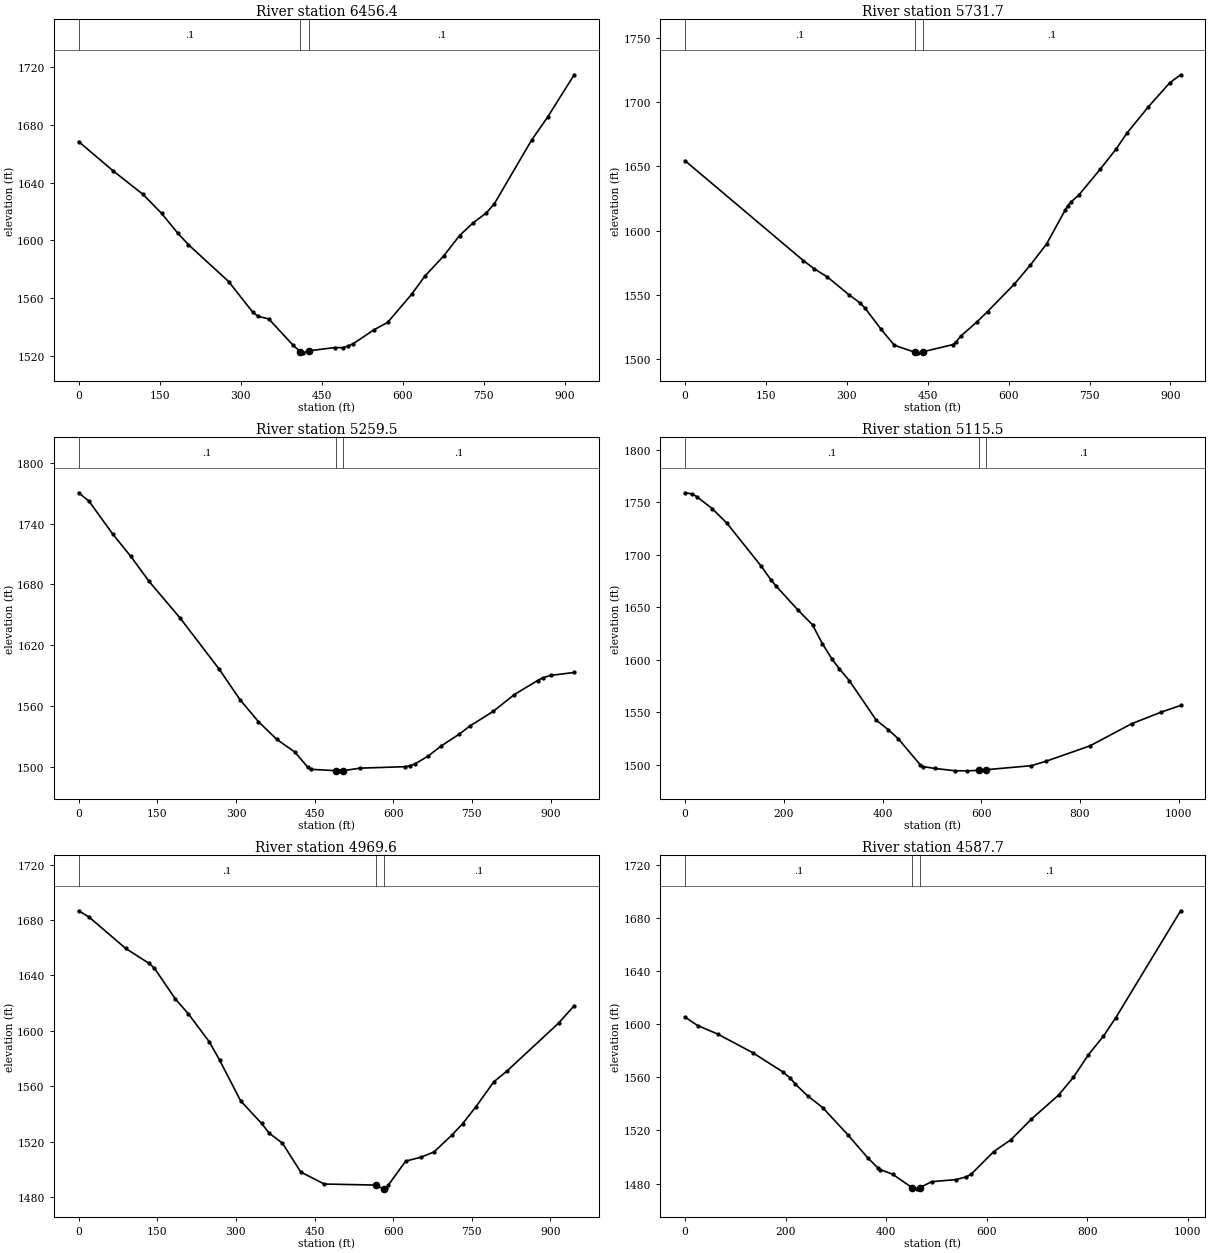
Type RM Length L Ch R = 1 ,6456.4  ,721.8,724.8,727.7
XS GIS Cut Line= 4
     1821161.272      254874.014     1821233.094      255239.079
     1821271.076      255395.226     1821322.395      255776.919
#Sta/Elev= 30
       0 1668.38    64.5 1647.89   119.1 1631.82   153.8 1618.56   183.6 1604.93
   203.4 1596.91   277.8 1571.38   322.4 1550.17   332.4 1547.25   352.2 1545.44
   396.4 1527.55   410.8 1522.66   415.9 1521.94   425.8 1523.31   474.3 1525.58
   488.9 1525.53   498.7 1526.55   508.4 1528.23   547.6 1538.03   572.3 1543.01
   616.7 1562.48   641.4 1575.12     676 1589.02   705.6 1603.23   730.3 1611.92
     755 1618.84   769.8 1625.11   838.9 1669.32   868.5 1685.21   917.9 1714.68
#Mann= 3 , 0 , 0
       0      .1       0   410.8    .045       0   425.8      .1       0
Bank Sta=410.8,425.8
XS Rating Curve= 0 ,0
Exp/Cntr=0.3,0.1

Type RM Length L Ch R = 1 ,5731.7  ,479.3,472.2,465.1
XS GIS Cut Line= 4
     1820642.265      255023.848      1820543.09      255342.474
     1820566.301      255553.484     1820728.779      255888.991
#Sta/Elev= 30
       0 1654.45   219.2 1576.78   239.1 1570.47     264 1563.94   303.8 1550.17
   323.7 1544.07   333.7 1539.72   363.3 1523.33     388 1510.84   425.4 1505.51
   432.4 1504.95   440.4 1505.73   496.6 1511.36   501.6 1513.16   511.4 1518.07
     541 1528.98   560.9 1537.12   610.6 1558.49   640.4  1573.4   670.2 1589.66
     705 1616.27     710 1619.58     715 1622.18   729.9 1627.72   769.6 1647.82
   799.5 1663.76   819.4 1676.06   859.1 1696.51   898.9 1715.25   918.8 1721.37
#Mann= 3 , 0 , 0
       0      .1       0   425.4    .045       0   440.4      .1       0
Bank Sta=425.4,440.4
XS Rating Curve= 0 ,0
Exp/Cntr=0.3,0.1

Type RM Length L Ch R = 1 ,5259.5  ,137.3,143.9,150.6
XS GIS Cut Line= 4
     1820116.849      255129.353     1820097.858      255566.145
     1820180.152      255747.614     1820424.924      255935.413
#Sta/Elev= 30
       0 1770.35    19.9 1762.08    64.6 1729.95    99.4 1707.76   134.1 1683.24
   193.8 1646.77   268.3 1596.42     308 1566.34   342.8 1544.97   377.6 1527.55
   412.4 1514.89   437.2 1499.82   442.2 1497.96   490.1 1496.59     497 1496.43
   505.1 1496.64   536.8 1499.08   621.5  1500.5   631.5 1501.28   641.4 1503.29
   666.3 1510.86   691.2 1520.87     726 1532.65   745.9 1540.48   790.7 1555.03
   830.5 1571.42   875.3 1585.42   885.3  1588.1   900.2 1590.46     945 1593.34
#Mann= 3 , 0 , 0
       0      .1       0   490.1    .045       0   505.1      .1       0
Bank Sta=490.1,505.1
XS Rating Curve= 0 ,0
Exp/Cntr=0.3,0.1

Type RM Length L Ch R = 1 ,5115.5  ,120,146,171.9
XS GIS Cut Line= 4
     1820056.096      255086.383     1819990.242      255648.439
     1820000.793      255728.623     1820058.261      256081.067
#Sta/Elev= 30
       0 1759.13    14.9 1757.99    24.8 1755.05    54.6 1744.16    84.4 1730.35
   153.9 1689.42   173.7 1676.42   183.7 1670.64   228.4 1647.62   258.1 1633.44
     278 1615.52   297.8 1600.65   312.7 1591.39   332.6 1580.33   387.2 1542.64
     412 1533.43   431.9 1524.92   476.6 1499.98   481.5 1498.43   506.3 1496.65
     546  1494.5   570.7 1494.37     595  1494.8     610 1495.45   701.3 1499.27
   731.1 1503.48   820.4  1518.2   904.7 1539.24   964.2 1550.21  1003.9 1556.66
#Mann= 3 , 0 , 0
       0      .1       0     595    .045       0     610      .1       0
Bank Sta=595,610
XS Rating Curve= 0 ,0
Exp/Cntr=0.3,0.1

Type RM Length L Ch R = 1 ,4969.6  ,391.8,381.8,371.9
XS GIS Cut Line= 4
      1819950.15      255112.472     1819901.618      255633.668
     1819808.773      255692.751     1819760.241      256000.827
#Sta/Elev= 30
       0  1686.6    19.9 1682.07    89.7 1659.43   134.6 1648.55   144.6 1645.15
   184.4 1622.99   209.4  1612.2   249.3 1591.98   269.2 1578.63   309.1 1549.34
     349 1533.09   363.9 1525.89   388.8 1518.85   423.8 1497.97   468.6 1489.32
   566.7 1488.57   580.9 1485.85   581.7 1485.93   585.6 1486.32   590.4 1488.32
   623.9 1505.83   653.3 1508.74     678  1512.5   712.7 1524.85   732.5 1532.87
   757.3 1544.78   791.9 1563.04   816.7 1570.74   915.7 1605.52   945.4 1618.05
#Mann= 3 , 0 , 0
       0      .1       0   566.7    .045       0   581.7      .1       0
Bank Sta=566.7,581.7
XS Rating Curve= 0 ,0
Exp/Cntr=0.3,0.1

Type RM Length L Ch R = 1 ,4587.7  ,135.4,122.8,110.2
XS GIS Cut Line= 4
     1819843.544      254994.221     1819658.956      255346.694
     1819580.882       255458.53     1819415.406      255878.351
#Sta/Elev= 30
       0 1605.18    24.9 1598.88    64.7 1592.48   134.3 1578.48     194 1564.08
   208.9 1559.44   218.8 1554.96   243.7    1546   273.5 1537.17   323.3 1516.84
   363.1 1499.39     383 1491.93   387.9 1490.47   412.5 1487.07   451.5 1476.87
   461.2 1476.02   466.5 1476.84   490.4 1481.43   539.2 1482.98   559.1 1485.05
     569 1487.03   613.6 1503.99   648.3 1513.06     688 1528.24   742.6 1546.49
   772.3 1559.95     802 1576.85   831.8  1590.8   856.6 1604.79   985.5  1685.2
#Mann= 3 , 0 , 0
       0      .1       0   451.5    .045       0   466.5      .1       0
Bank Sta=451.5,466.5
XS Rating Curve= 0 ,0
Exp/Cntr=0.3,0.1