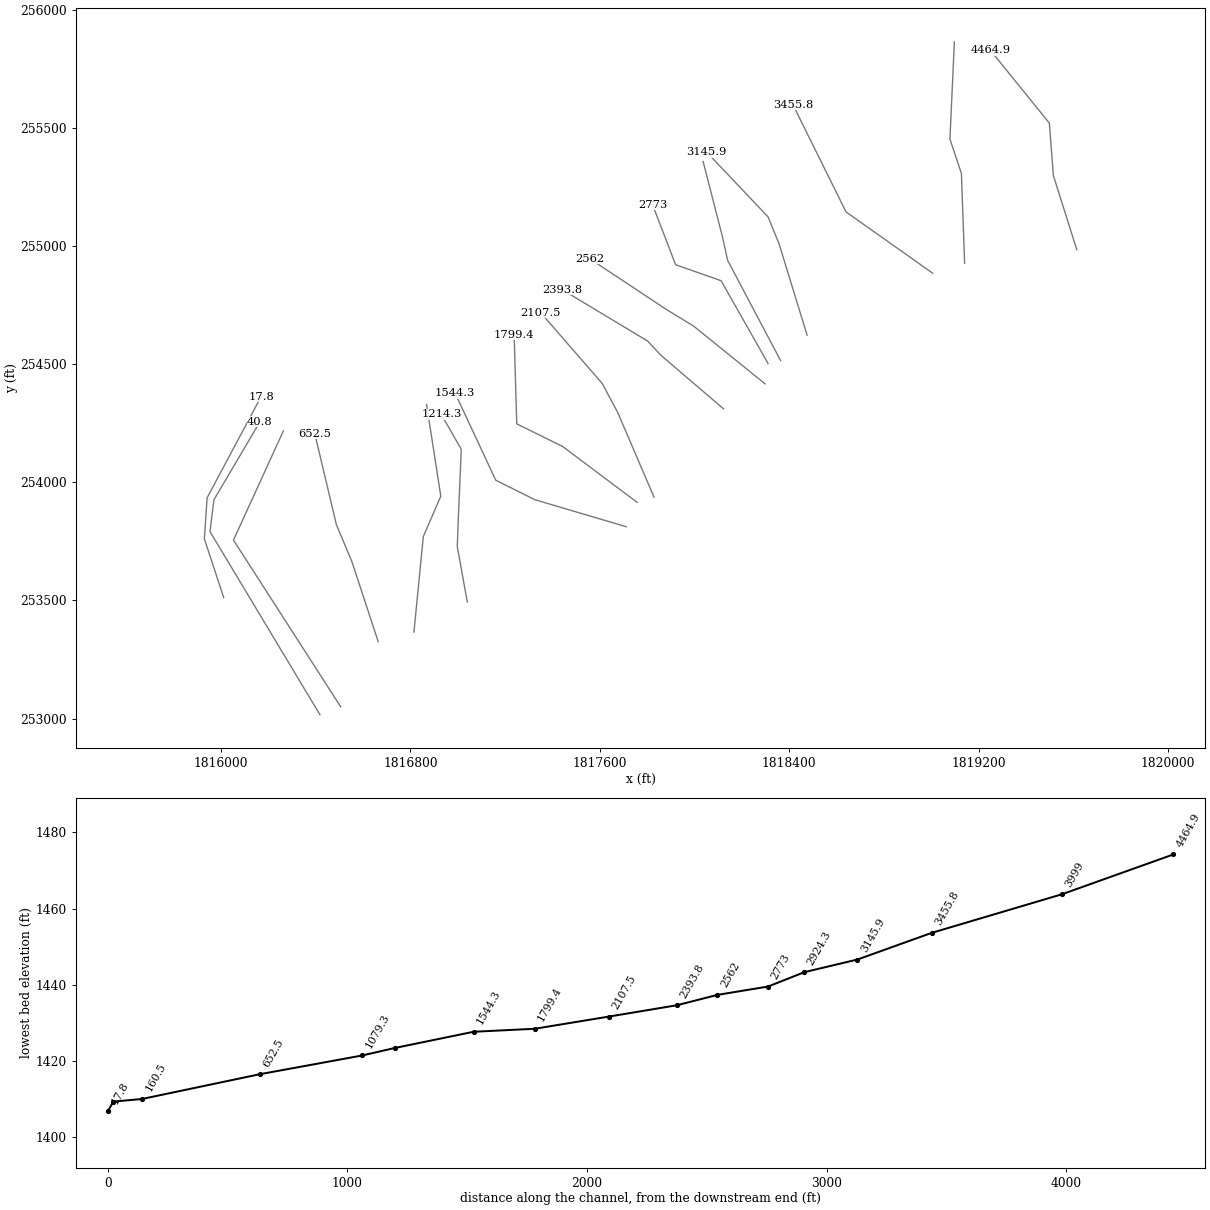
HEC-RAS study GlenFk.prj: GlenFk

--- GlenFk.g01 (geometry) --- (continued)

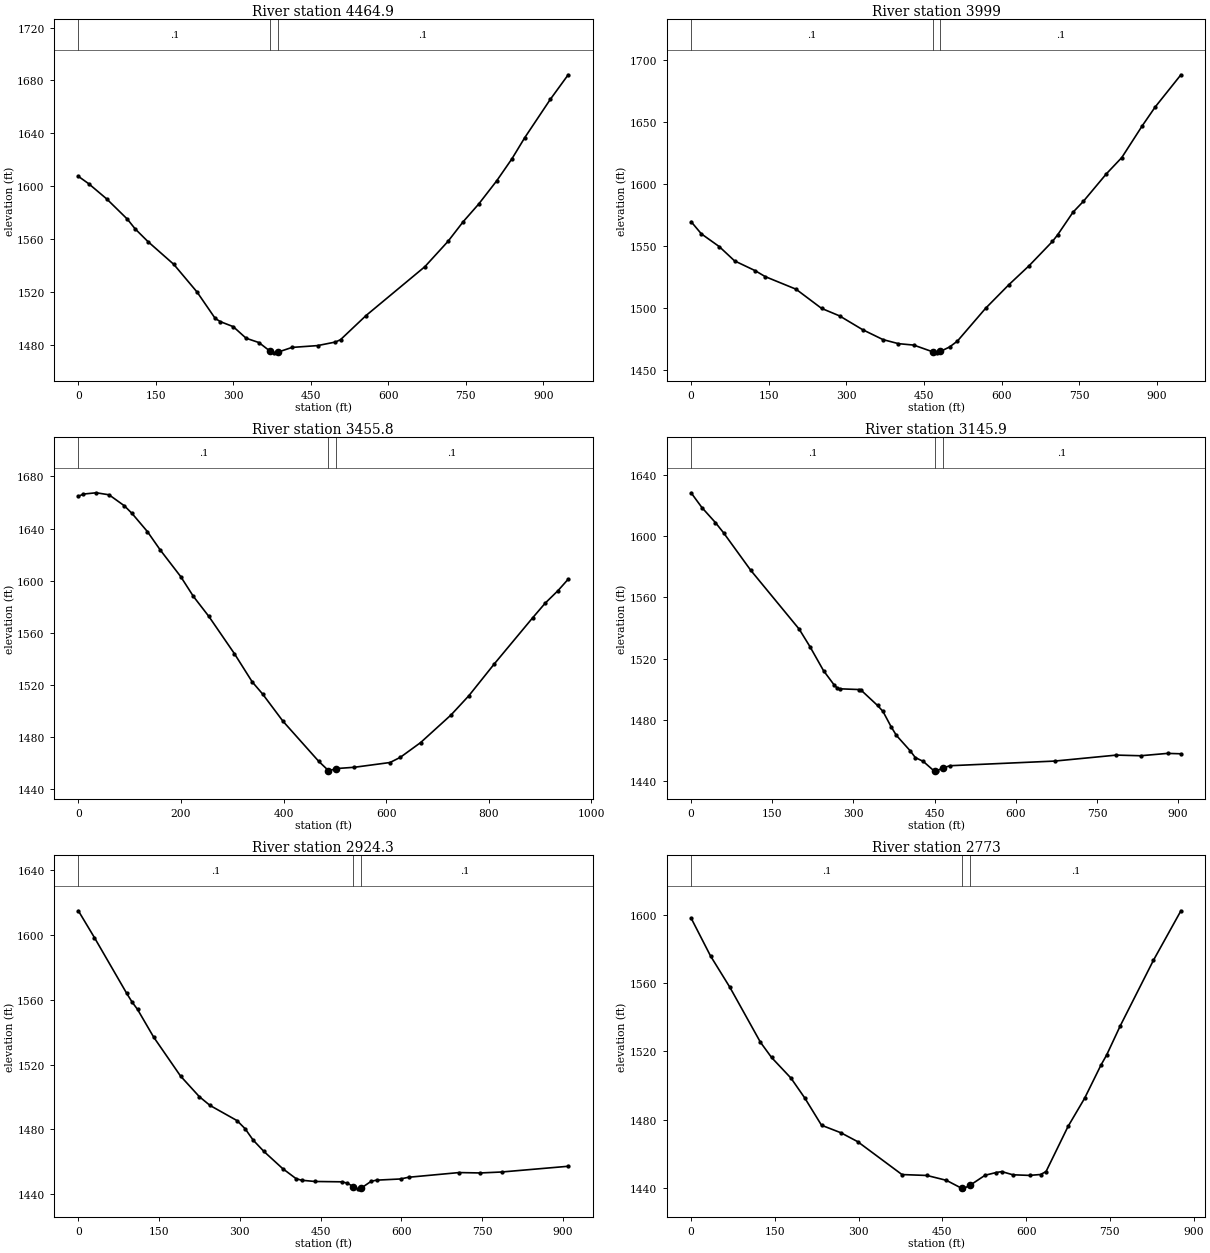
Type RM Length L Ch R = 1 ,4464.9  ,459.7,465.8,472
XS GIS Cut Line= 4
     1819614.644      254983.756     1819515.469      255298.162
     1819498.588      255519.723     1819249.595      255827.798
#Sta/Elev= 30
       0 1607.58      20 1602.02      55 1590.48    94.9 1575.22   109.9 1567.91
   134.9 1558.22   184.8 1541.06   229.8 1520.16   264.7 1500.33   274.7 1497.84
   299.7 1494.05   324.7 1485.28   349.4 1482.03   371.8 1475.28   379.1 1474.25
   386.8 1474.85   413.6 1478.35     463 1479.72   497.6 1482.42   507.4 1484.19
   556.8 1502.43   670.7 1539.36   715.3 1558.41     745  1573.4   774.7  1586.6
   809.4 1604.05   839.1 1620.81   863.8 1636.71   913.3 1665.67     948  1684.3
#Mann= 3 , 0 , 0
       0      .1       0   371.8    .045       0   386.8      .1       0
Bank Sta=371.8,386.8
XS Rating Curve= 0 ,0
Exp/Cntr=0.3,0.1

Type RM Length L Ch R = 1 ,3999    ,540.8,543.2,545.7
XS GIS Cut Line= 4
     1819140.738      254926.359     1819127.209      255306.602
     1819078.677      255452.199     1819097.433      255863.682
#Sta/Elev= 30
       0 1569.54    19.8  1559.7    54.4 1549.42      84  1537.9   123.5 1530.07
   143.3  1525.2   202.6 1515.09     252 1499.61   286.6 1493.59   331.1 1482.49
   370.6 1474.46   400.3  1471.2     430 1470.03   466.5 1464.63   474.6 1463.79
   481.5 1464.93   499.3 1468.55   514.2 1473.23   568.7 1499.68   613.4  1518.6
   653.1 1534.16   697.7 1553.53   707.6 1558.77   737.4 1577.07   757.3 1585.79
     802  1608.1   831.7 1621.18   871.4 1646.89   896.2 1661.94   945.9  1687.9
#Mann= 3 , 0 , 0
       0      .1       0   466.5    .045       0   481.5      .1       0
Bank Sta=466.5,481.5
XS Rating Curve= 0 ,0
Exp/Cntr=0.3,0.1

Type RM Length L Ch R = 1 ,3455.8  ,311.5,309.9,308.3
XS GIS Cut Line= 3
     1819005.777      254884.736     1818639.775      255144.124
     1818415.563      255597.725
#Sta/Elev= 30
       0 1664.78      10 1666.49    34.9 1667.47    59.8 1665.92    89.7 1657.46
   104.7 1651.55   134.6 1637.62   159.5 1623.55   199.4 1603.08   224.3 1587.75
   254.2 1572.48     304 1543.86   338.9 1522.04   358.9 1512.84   398.8 1491.81
   468.4 1461.01   487.3 1453.91   488.3 1453.67   502.3 1455.41   537.9 1456.41
   607.3 1460.07   627.2 1463.99   666.9 1475.36   726.4 1496.68   761.1 1511.46
   810.7 1535.94   885.1 1571.22   909.9 1582.64   934.7 1592.21   954.6 1601.01
#Mann= 3 , 0 , 0
       0      .1       0   487.3    .045       0   502.3      .1       0
Bank Sta=487.3,502.3
XS Rating Curve= 0 ,0
Exp/Cntr=0.3,0.1

Type RM Length L Ch R = 1 ,3145.9  ,225.5,221.6,217.7
XS GIS Cut Line= 4
     1818475.519      254622.308     1818357.021      255009.077
     1818310.598      255123.023     1818051.055      255397.337
#Sta/Elev= 30
       0 1628.33      20 1618.68      45 1608.85    59.9 1602.25   109.9 1577.85
   199.8 1539.22   219.7  1527.8   244.7 1512.14   264.7 1502.63   269.7 1500.95
   274.7 1500.27   309.6  1499.8   314.6 1499.24   344.6 1489.37   354.6  1485.5
   369.6  1475.5   379.5 1469.79   404.5 1459.93   414.4 1455.34   429.1 1452.83
   448.8 1446.68   449.9 1446.68   453.7  1446.7   464.9 1448.46   478.3 1450.02
   671.6 1453.05   785.9 1456.96   830.7 1456.54   880.4 1458.08   905.2 1457.82
#Mann= 3 , 0 , 0
       0      .1       0   449.9    .045       0   464.9      .1       0
Bank Sta=449.9,464.9
XS Rating Curve= 0 ,0
Exp/Cntr=0.3,0.1

Type RM Length L Ch R = 1 ,2924.3  ,128.4,151.3,174.4
XS GIS Cut Line= 4
     1818363.351      254515.313      1818139.68      254939.444
     1818118.579      255036.509     1818036.285      255357.244
#Sta/Elev= 30
       0 1614.92      30 1598.31    89.9 1563.93    99.9 1558.57   109.9 1554.09
   139.8 1537.04   189.8 1512.97   224.8 1500.22   244.7  1494.8   294.7 1485.48
   309.7  1480.5   324.7 1473.46   344.6 1466.48   379.6 1455.84   404.6 1449.63
   414.6 1448.67   439.5  1447.9   489.4 1447.69   499.4 1446.89   510.8 1444.74
   519.2 1443.36   525.8 1443.89   544.1 1448.03     554 1448.72   598.6 1449.45
   613.4  1450.5   707.3  1453.4   746.9 1453.16   786.4 1453.75     910 1457.28
#Mann= 3 , 0 , 0
       0      .1       0   510.8    .045       0   525.8      .1       0
Bank Sta=510.8,525.8
XS Rating Curve= 0 ,0
Exp/Cntr=0.3,0.1

Type RM Length L Ch R = 1 ,2773    ,215.6,211,206.3
XS GIS Cut Line= 4
     1818310.598      254502.652     1818112.249      254852.929
     1817920.229      254920.453     1817823.164      255173.665
#Sta/Elev= 30
       0  1598.1    34.8 1575.92    69.6  1557.5   124.2 1525.41   144.1 1516.49
   178.9  1504.4   203.8 1492.67   233.6 1476.82   268.4  1472.4   298.2 1467.24
   377.7 1447.95   422.4 1447.42   457.2 1444.58   484.4 1439.95   486.9 1439.59
   499.4 1441.64   526.6 1447.55   546.5 1449.15   556.4 1449.68   576.3 1447.82
   606.1 1447.46   625.8 1447.98   635.7 1449.69   675.1  1476.1   704.7 1492.54
   734.3 1512.17   744.1 1517.82   768.8 1535.12     828 1573.34   877.3 1602.36
#Mann= 3 , 0 , 0
       0      .1       0   484.4    .045       0   499.4      .1       0
Bank Sta=484.4,499.4
XS Rating Curve= 0 ,0
Exp/Cntr=0.3,0.1

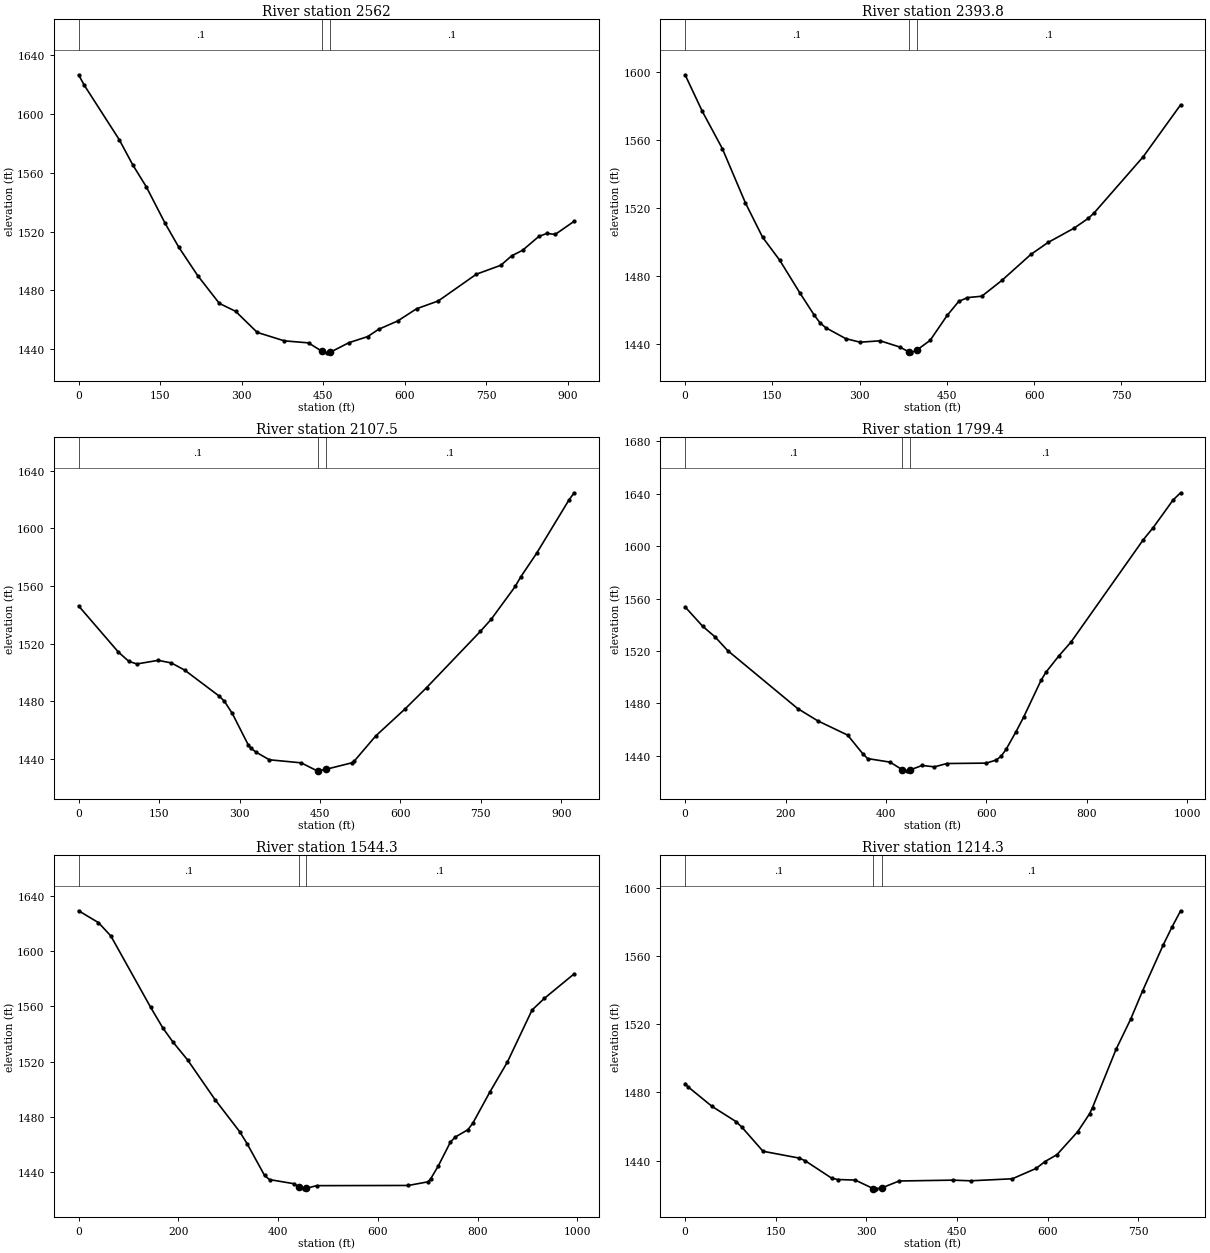
Type RM Length L Ch R = 1 ,2562    ,174.4,168.3,162.1
XS GIS Cut Line= 4
     1818298.066      254416.591     1817996.193       254660.91
     1817882.247      254730.543     1817557.422      254946.172
#Sta/Elev= 30
       0 1626.74      10 1619.85    74.7 1582.58    99.6  1565.4   124.5 1550.47
   159.3 1525.49   184.2 1509.38   219.1 1489.98   258.9 1471.08   288.8 1465.69
   328.6 1451.33   378.4 1445.58     423 1444.19   447.9 1438.41   457.6 1437.41
   462.9 1437.79   497.2  1444.3   531.9 1448.48   551.9 1453.42   586.9 1459.08
   621.9 1467.44   661.8 1472.75   731.8 1490.95   776.8 1497.03   796.8 1503.48
   816.8 1507.21   846.8 1516.68   861.8 1518.74   876.8 1518.01   911.8 1526.99
#Mann= 3 , 0 , 0
       0      .1       0   447.9    .045       0   462.9      .1       0
Bank Sta=447.9,462.9
XS Rating Curve= 0 ,0
Exp/Cntr=0.3,0.1

Type RM Length L Ch R = 1 ,2393.8  ,292.1,286.3,280.4
XS GIS Cut Line= 4
     1818122.799      254310.632     1817856.926      254538.524
     1817802.063      254597.607     1817441.235      254814.947
#Sta/Elev= 30
       0 1598.64    29.6 1577.06    64.1 1555.06   103.6 1523.19   133.2 1502.88
   162.8 1489.23   197.3 1470.05   221.9 1456.99   231.8 1452.48   241.7 1449.54
   276.2 1443.08   300.9 1440.97   335.4  1441.8   369.2 1438.11   384.2 1435.35
   388.1  1434.7   399.2 1436.49   421.3 1442.07   450.6 1456.76   470.4 1464.98
   485.3 1467.26   510.1 1468.08   544.8 1477.44   594.3 1492.68   624.1 1499.78
   668.7 1508.19   693.4 1514.04   703.4 1517.25   787.6  1550.3     852 1580.95
#Mann= 3 , 0 , 0
       0      .1       0   384.2    .045       0   399.2      .1       0
Bank Sta=384.2,399.2
XS Rating Curve= 0 ,0
Exp/Cntr=0.3,0.1

Type RM Length L Ch R = 1 ,2107.5  ,294.1,308.1,322.2
XS GIS Cut Line= 4
     1817829.011      253937.146     1817675.457      254295.861
     1817610.043      254418.248     1817351.278      254716.671
#Sta/Elev= 30
       0  1546.2    74.1 1514.16    93.8 1507.65   108.7 1505.92   148.2 1508.41
   172.9 1506.62   197.6 1501.66   261.8 1483.68   271.7 1480.06   286.5 1471.57
   316.1 1449.85     321  1447.5   330.9 1444.65   355.6 1439.38     415 1437.25
   444.7  1431.7   446.3 1431.73   461.3 1432.77   509.2 1437.25   514.1 1438.54
     554 1455.94     609  1474.8     649 1489.56     749 1528.49     769  1536.8
     814 1559.69     824 1566.15     854 1582.78     914  1619.6     924 1624.76
#Mann= 3 , 0 , 0
       0      .1       0   446.3    .045       0   461.3      .1       0
Bank Sta=446.3,461.3
XS Rating Curve= 0 ,0
Exp/Cntr=0.3,0.1

Type RM Length L Ch R = 1 ,1799.4  ,255.2,255.1,254.9
XS GIS Cut Line= 4
     1817757.341      253915.338     1817442.935       254151.67
     1817249.215      254247.329     1817238.255      254624.333
#Sta/Elev= 30
       0  1553.6    34.8 1538.88    59.8 1530.68    84.6 1520.32     224 1476.07
   263.9 1466.71   323.6 1455.78   353.5 1441.66   363.4 1437.88     408 1435.16
   432.7  1429.3   442.4 1428.52   447.7 1429.19   471.9 1432.63   496.4 1431.55
     521  1434.1   599.6 1434.41   619.3 1436.76   629.2  1439.7   639.2 1445.03
     659 1458.53   673.9 1469.46   708.6 1497.58   718.6 1503.88   743.4 1515.89
   768.2 1526.75   912.1 1604.83     932 1614.17   971.6 1635.23   986.5 1640.66
#Mann= 3 , 0 , 0
       0      .1       0   432.7    .045       0   447.7      .1       0
Bank Sta=432.7,447.7
XS Rating Curve= 0 ,0
Exp/Cntr=0.3,0.1

Type RM Length L Ch R = 1 ,1544.3  ,356.3,330,303.7
XS GIS Cut Line= 4
     1817711.305      253812.235     1817325.179      253926.593
     1817160.591      254008.887     1816988.541       254377.78
#Sta/Elev= 30
       0 1629.34    39.8 1620.75    64.6 1611.08   144.2 1559.48     169 1544.32
   188.9  1534.3   218.8 1521.07   273.4  1492.5   323.2 1469.06   338.1 1460.34
   372.9 1437.41   382.8 1434.44   432.6 1431.39   441.2 1428.94   452.4 1427.73
   456.2 1428.07   477.3 1430.04   661.2 1430.18   700.9 1432.84   705.8 1434.87
   720.8    1444   745.6 1461.62   755.5 1465.35   780.3 1470.49   790.2 1475.12
     825  1498.1   859.7 1519.55   909.4 1557.42   934.2 1565.89   993.8 1583.62
#Mann= 3 , 0 , 0
       0      .1       0   441.2    .045       0   456.2      .1       0
Bank Sta=441.2,456.2
XS Rating Curve= 0 ,0
Exp/Cntr=0.3,0.1

Type RM Length L Ch R = 1 ,1214.3  ,142,135.1,128
XS GIS Cut Line= 5
     1817040.315      253494.021     1816998.113      253728.243
     1817002.333      253844.299     1817014.994      254139.714
     1816930.589      254287.421
#Sta/Elev= 30
       0  1485.2       5 1483.26    44.6 1471.79    84.3 1462.89    94.2 1459.52
   128.9  1445.5   188.4 1441.52   198.3    1440   242.8 1429.66   252.5 1428.93
   281.5  1428.6   311.4 1423.58   315.4 1423.46   326.4 1424.14   354.1 1428.06
   442.8 1428.56   472.4 1428.17   541.4 1429.36   580.8 1435.44   595.6 1439.49
   615.3 1443.51   649.8 1457.08   669.2 1467.47   674.1 1471.15     713 1505.24
   737.3 1523.02   756.8 1539.44   790.8 1566.29   805.4 1576.86   819.9 1586.53
#Mann= 3 , 0 , 0
       0      .1       0   311.4    .045       0   326.4      .1       0
Bank Sta=311.4,326.4
XS Rating Curve= 0 ,0
Exp/Cntr=0.3,0.1

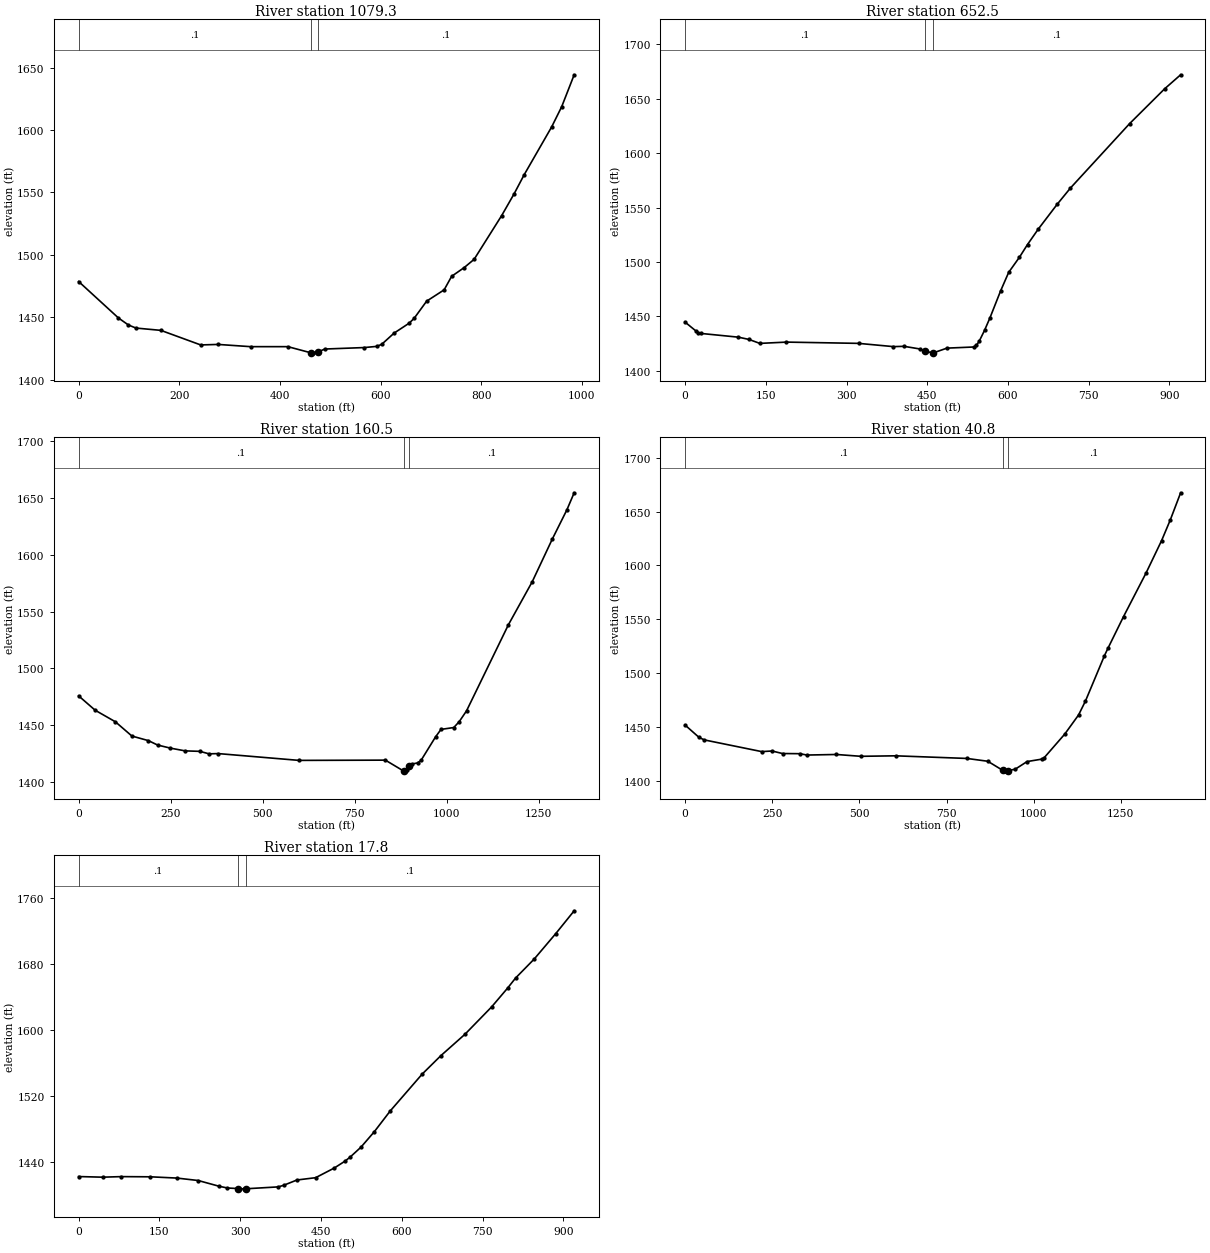
Type RM Length L Ch R = 1 ,1079.3  ,410.1,426.8,443.4
XS GIS Cut Line= 4
     1816815.042      253366.356     1816854.626      253770.445
     1816928.479      253941.364     1816868.437      254329.333
#Sta/Elev= 30
       0 1478.64    79.2  1449.4      99  1443.8   113.9 1441.36   163.4 1439.51
   242.6 1427.84   277.3 1428.24   341.6 1426.46   415.8 1426.46     461  1421.6
   464.8 1421.51     476 1422.31   489.3 1424.56   567.7 1425.74   592.2 1426.67
   602.2 1428.29     627 1437.34   656.8 1445.24   666.8 1449.17   691.6  1462.9
   726.4 1471.97   741.3 1482.81   766.2 1489.78     786 1496.42   840.7 1531.43
   865.5 1548.92   885.4 1564.13   940.1 1602.49     960 1618.66   984.8 1644.22
#Mann= 3 , 0 , 0
       0      .1       0     461    .045       0     476      .1       0
Bank Sta=461,476
XS Rating Curve= 0 ,0
Exp/Cntr=0.3,0.1

Type RM Length L Ch R = 1 ,652.5   ,514.1,492,472.7
XS GIS Cut Line= 4
     1816664.187      253325.681      1816552.88       253664.94
     1816487.467      253821.088     1816396.533      254204.826
#Sta/Elev= 30
       0 1444.83    19.8 1436.82    24.8 1435.18    29.8 1434.41    99.2 1430.99
     119 1428.87   138.8 1425.28   188.4 1426.47   322.3  1425.3   386.9 1422.32
   406.8 1422.58   436.7 1420.12   446.4 1417.86   461.4  1416.6   486.5 1420.93
   536.3 1421.97   541.3 1423.47   546.3 1427.16   556.3  1437.2   566.3 1448.61
   586.2 1473.52   601.2 1490.56   621.2 1504.46   636.2 1516.16   656.1 1530.27
   691.1 1552.99     716 1568.09   825.9 1627.26   890.8 1659.17   920.7 1672.15
#Mann= 3 , 0 , 0
       0      .1       0   446.4    .045       0   461.4      .1       0
Bank Sta=446.4,461.4
XS Rating Curve= 0 ,0
Exp/Cntr=0.3,0.1

Type RM Length L Ch R = 1 ,160.5   ,107,119.7,126.6
XS GIS Cut Line= 4
     1816505.885      253050.066     1816052.786      253755.674
     1816099.208       253856.96     1816263.796      254217.788
#Sta/Elev= 30
       0 1475.95    44.9 1463.34    99.8  1453.2   144.8 1440.66   189.7 1436.62
   214.6 1432.76   249.6 1430.03   289.5 1427.63   329.4 1427.22   354.4 1425.04
   379.4 1425.25     599 1419.28   833.6  1419.5   882.2  1410.1   884.1 1410.22
   891.8 1411.17   899.1 1413.98   906.4 1416.15   920.9 1417.03   930.6 1419.35
   969.8 1439.87   984.7 1446.49  1019.4 1448.14  1034.2 1453.29  1054.1 1462.79
  1168.1 1538.55  1232.6 1576.18  1287.1 1613.64  1326.7 1639.28  1346.6 1654.34
#Mann= 3 , 0 , 0
       0      .1       0   884.1    .045       0   899.1      .1       0
Bank Sta=884.1,899.1
XS Rating Curve= 0 ,0
Exp/Cntr=0.3,0.1

Type RM Length L Ch R = 1 ,40.8    ,27.3,23,24.3
XS GIS Cut Line= 4
     1816417.971      253016.938     1815953.611      253791.546
     1815970.491      253926.593      1816164.51        254255.8
#Sta/Elev= 30
       0 1451.88    39.9 1440.46    54.9 1438.12   219.6 1427.26   249.5 1427.82
   279.4 1425.47   329.3 1425.32   349.3 1424.06   434.1 1424.59     504 1422.89
   603.8 1423.35   808.3 1420.91   868.2  1418.3   910.5 1409.98   917.7 1409.41
   925.5 1409.58   946.9 1410.93   980.9 1418.01  1024.6 1420.35  1029.5  1421.4
  1088.9 1443.47  1128.6 1461.24  1148.4 1474.19    1203 1516.37  1212.9 1523.13
  1257.6 1552.54  1322.1 1592.92  1366.8 1623.05  1391.6 1642.13  1421.4 1667.41
#Mann= 3 , 0 , 0
       0      .1       0   910.5    .045       0   925.5      .1       0
Bank Sta=910.5,925.5
XS Rating Curve= 0 ,0
Exp/Cntr=0.3,0.1

Type RM Length L Ch R = 1 ,17.8    ,12.8,17.8,22.9
XS GIS Cut Line= 4
     1816011.527      253512.571     1815929.983      253761.024
      1815941.45      253934.304     1816169.517      254362.408
#Sta/Elev= 30
       0 1421.78    44.4 1421.02    78.9  1421.7   133.2 1421.47   182.6 1419.93
     222 1416.97   261.5 1409.87   276.4 1407.86   295.8 1407.19   306.2 1406.84
   310.8 1406.93   370.6 1409.21   380.6 1411.12   405.4 1417.59   440.1  1420.4
   474.8 1432.18   494.6  1440.5   504.4 1445.58   524.2 1457.47     549 1476.26
   578.7 1501.62   638.1 1546.49   672.7 1568.83   717.3 1594.76   766.8 1628.02
   796.5  1650.9   811.3 1663.14     846 1686.33   885.6 1716.92   920.2    1745
#Mann= 3 , 0 , 0
       0      .1       0   295.8    .045       0   310.8      .1       0
Bank Sta=295.8,310.8
XS Rating Curve= 0 ,0
Exp/Cntr=0.3,0.1

Chan Stop Cuts=-1
Use User Specified Reach Order=0